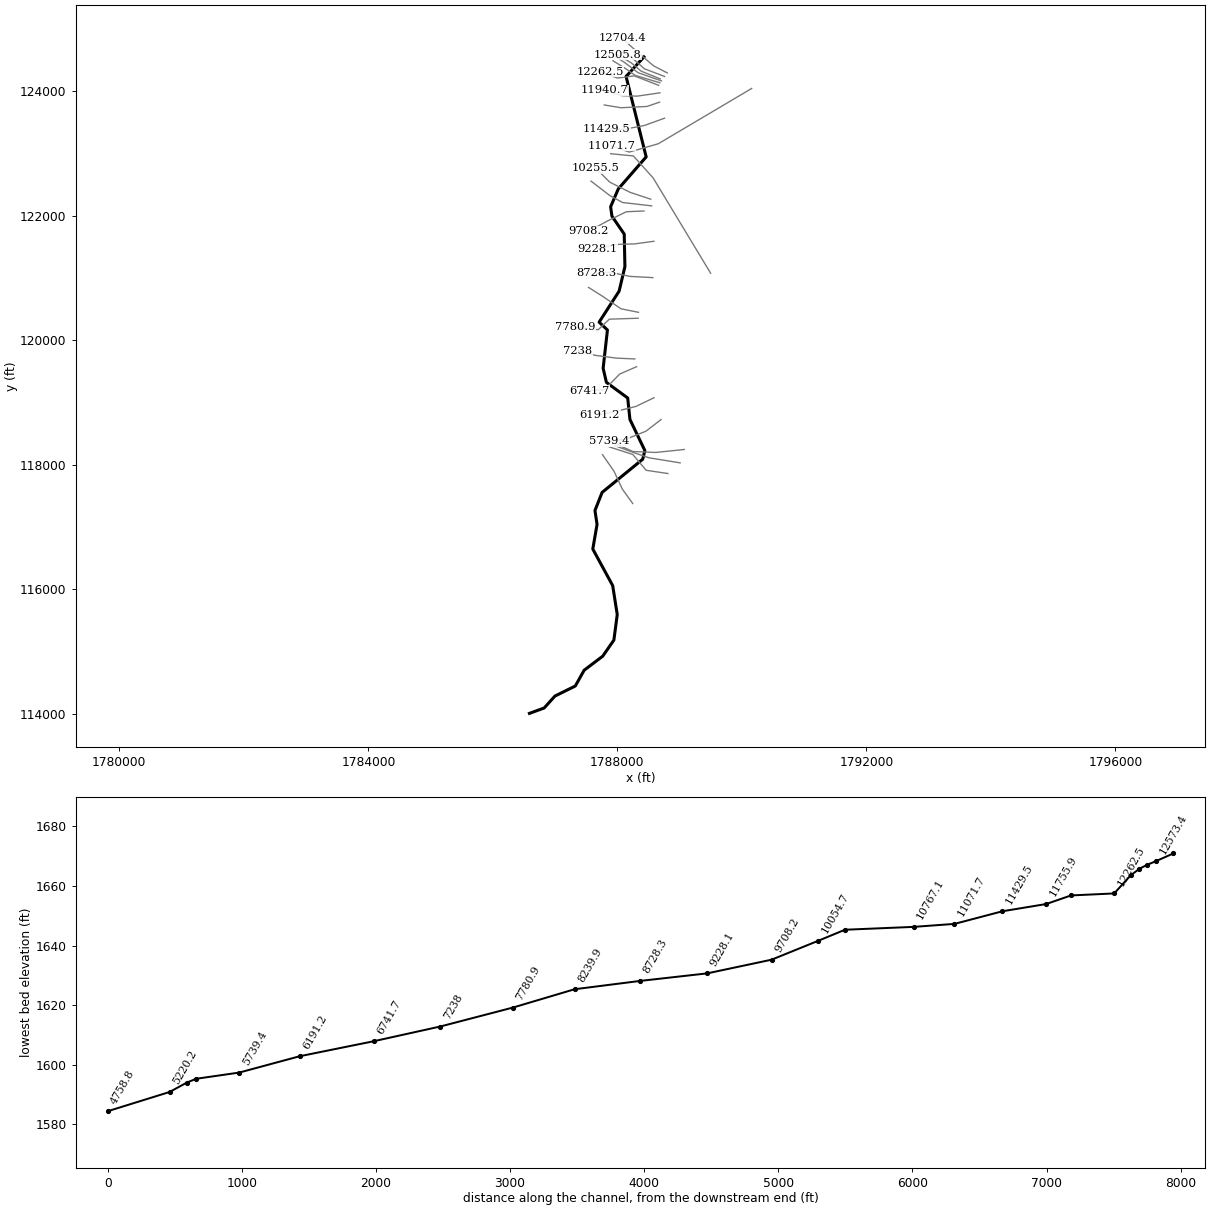
--- Mountain Fork.prj (project) ---

Proj Title=Mountain Fork
Current Plan=p01
Default Exp/Contr=0,0
English Units
Geom File=g01
Flow File=f01
Plan File=p01
BEGIN DESCRIPTION:
END DESCRIPTION:
DSS Export Rating Curves= 0
DSS Export Rating Curve Sorted= 0
DSS Export Volume Flow Curves= 0
DXF OffsetX= 0
DXF OffsetY= 0
DXF ScaleX= 0
DXF ScaleY= 0

--- Mountain Fork.p01 (plan) ---

Plan Title=Floodplain
Program Version=4.00
Geom File=g01
Flow File=f01
K Sum by GR=0
Std Step Tol=0.01
Critical Tol=0.01
Num of Std Step Trials=20
Max Error Tol=0.3
Flow Tol Ratio=0.001
Split Flow NTrial=30
Split Flow Tol=0.02
Split Flow Ratio=0.02
Log Output Level=0
Friction Slope Method=1
Unsteady Friction Slope Method=2
Unsteady Bridges Friction Slope Method=1
Global Log Level=0
CheckData=False
Run HTab=0
Run UNet=0
Run PostProcess=0
UNET Theta=0
UNET Theta Warmup=0
UNET ZTol=0
UNET ZSATol=0
UNET MxIter=0
UNET MaxInSteps=0
UNET DtIC=0
UNET DtMin=0
UNET MaxCRTS=0
UNET WFStab=0
UNET SFStab=0
UNET WFX=0
UNET SFX=0
UNET DSS MLevel=0
UNET DZMax Abort=0
UNET Convert EG Bridges=0
UNET Use Existing IB Tables=0
UNET Froude Limit=0
UNET Froude Power=0
Write IC File=0
Echo Input=False
Echo Output=False
Write Detailed=0

--- Mountain Fork.f01 (steady flow) ---

Flow Title=NFF Regression Equation
Program Version=4.00
Number of Profiles=1
Profile Names=P100yr
River Rch & RM=Mountain Fork,Main      ,12704.4
540.4370
River Rch & RM=Mountain Fork,Main      ,12573.4
571.8093
River Rch & RM=Mountain Fork,Main      ,12262.5
707.5087
River Rch & RM=Mountain Fork,Main      ,11071.7
735.3685
River Rch & RM=Mountain Fork,Main      ,10767.1
1485.147
River Rch & RM=Mountain Fork,Main      ,8239.9
1572.233
Boundary for River Rch & Prof#=Mountain Fork,Main      ,1
Up Type=0
Dn Type=3
Dn Slope=0.017461

--- Mountain Fork.g01 (geometry) ---

Geom Title=USGS 10m DEM
Program Version=4.00

River Reach=Mountain Fork   ,Main
Reach XY= 30
     1788426.418       124552.79     1788139.237      124238.686
     1788462.179       122946.92     1788014.015      122432.191
     1787891.429      122146.156      1787911.86       121995.89
     1788109.682      121707.136     1788120.675      121184.701
     1788027.759      120790.739     1787706.232      120292.208
     1787840.022      120166.986      1787770.82       119551.42
     1787823.545      119325.361     1788165.599      119074.257
     1788201.189      118730.225     1788441.088      118229.996
     1788406.817      118090.933     1787754.343      117557.749
     1787639.666      117267.102     1787673.278      117043.679
     1787604.736      116648.241     1787924.382      116061.014
     1787997.538      115595.715     1787943.495      115185.777
     1787764.229      114927.423     1787465.673      114701.364
     1787323.974      114448.284     1786997.078      114286.813
     1786823.744      114095.025     1786587.211      114008.689

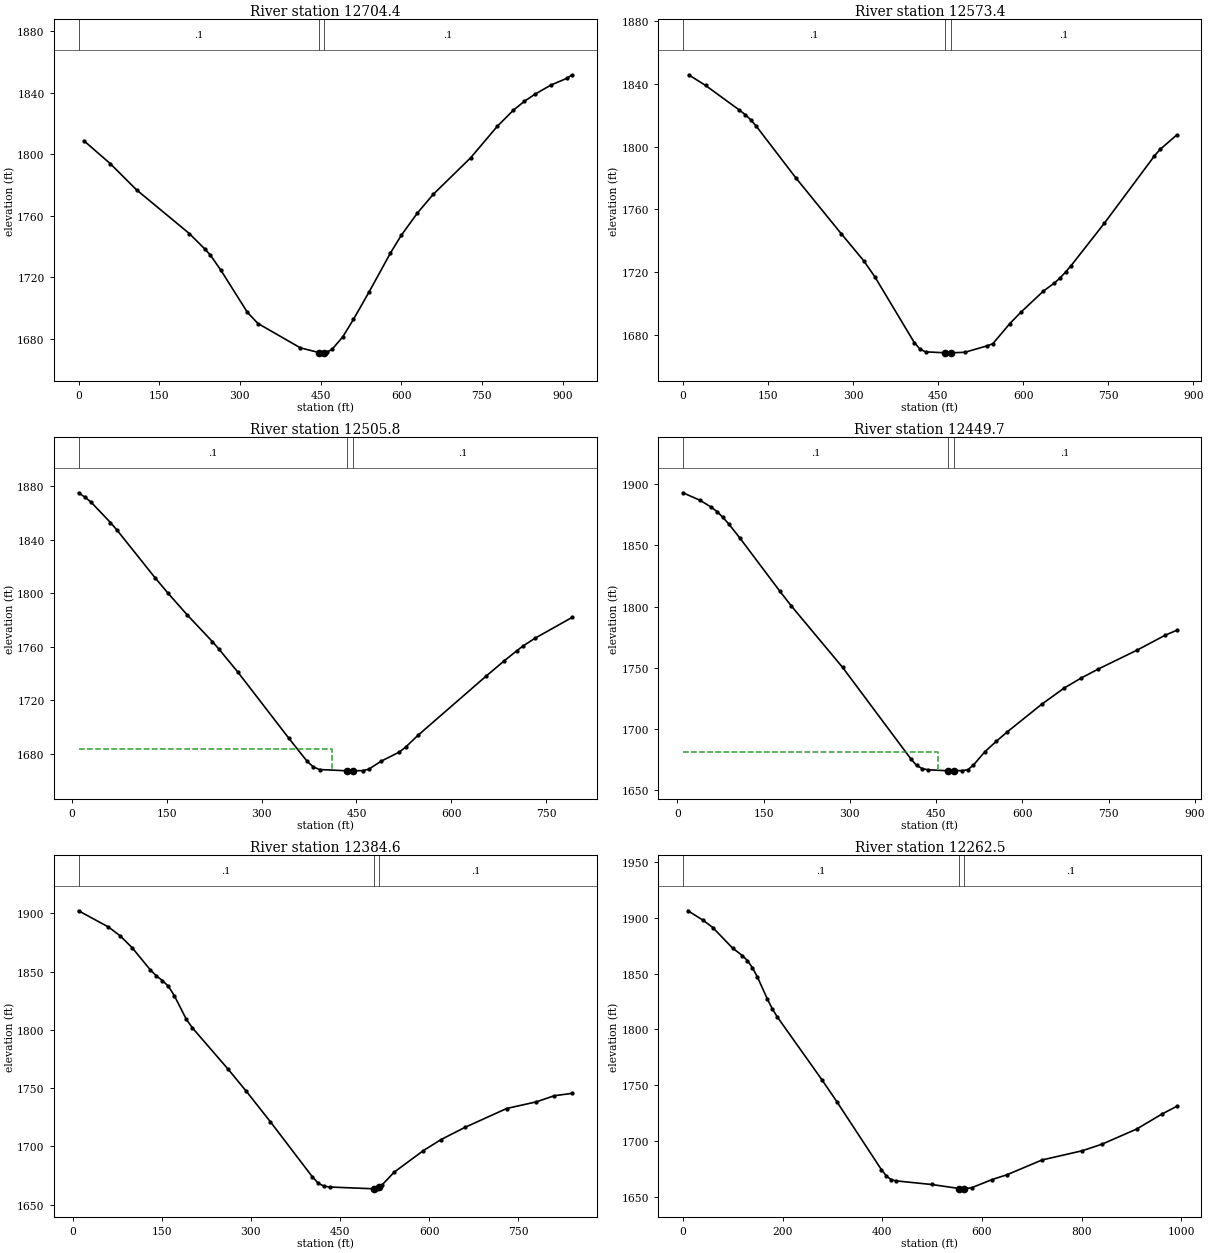
Type RM Length L Ch R = 1 ,12704.4 ,131.5,131,130.5
XS GIS Cut Line= 4
     1788800.805      124295.941     1788582.973      124408.223
     1788327.627      124624.971     1788076.647      124851.219
#Sta/Elev= 30
     9.8 1808.83    58.8 1793.96   107.8 1776.87   205.9 1748.48   235.3 1738.24
   245.1 1734.48   264.8 1724.54     314 1697.21   333.7 1689.98   412.5 1674.15
   446.9 1671.11   451.9 1670.92   456.9 1671.13   461.8 1671.33   471.6 1673.27
   491.3 1681.32     511 1692.59   540.6 1710.73     580 1735.83   599.9 1747.21
   629.7 1761.64   659.5 1773.94   729.1 1797.71   778.8 1818.24   808.6 1828.64
   828.5 1834.29   848.3 1838.95   878.2 1844.93     908 1849.38   917.9 1851.65
#Mann= 3 , 0 , 0
       0      .1       0   446.9    .045       0   456.9      .1       0
Bank Sta=446.9,456.9
XS Rating Curve= 0 ,0
Exp/Cntr=0.3,0.1

Type RM Length L Ch R = 1 ,12573.4 ,67,67.5,68.1
XS GIS Cut Line= 4
     1788758.152      124238.983     1788432.278      124362.973
     1788217.769      124553.711     1788006.961      124657.631
#Sta/Elev= 30
      10 1845.96    39.8 1839.17    99.6 1823.39   109.6 1820.57   119.5 1817.21
   129.5 1813.04   199.2 1780.05   278.9 1744.54   318.8 1727.17   338.7 1716.75
   408.1 1674.83     418  1670.7   427.9 1668.95   462.4 1668.34   467.4 1668.31
   472.4 1668.33   497.1 1668.66   536.7  1672.8   546.6 1674.16   576.3 1686.91
   596.1 1694.28   635.7 1707.75   655.3 1712.97   665.1 1716.13   674.9 1719.93
   684.7 1724.07   743.4 1751.19   831.6 1794.15   841.4 1798.24   870.7 1807.43
#Mann= 3 , 0 , 0
       0      .1       0   462.4    .045       0   472.4      .1       0
Bank Sta=462.4,472.4
XS Rating Curve= 0 ,0
Exp/Cntr=0.3,0.1

Type RM Length L Ch R = 1 ,12505.8 ,55,56.2,57.3
XS GIS Cut Line= 4
     1788689.132      124199.297     1788380.412      124324.349
     1788224.108      124456.189     1788006.463      124587.014
#Sta/Elev= 30
    10.1 1875.26    20.2 1871.97    30.3 1868.05    60.6 1852.99    70.7 1847.49
   131.2 1811.63   151.4 1800.27   181.7 1784.02   222.1 1763.74   232.2 1758.25
   262.4 1740.92   342.8 1691.53     372 1674.12   381.8 1669.95   391.5 1668.01
   435.2 1667.07   440.2 1667.04   445.2 1667.07   459.7 1667.21   469.4 1668.21
   488.9 1674.22   518.1 1681.16   527.8 1684.79   547.3  1693.6   654.8 1737.81
   684.1  1749.5   703.6  1756.9   713.4 1760.45   732.9 1766.42   791.5 1781.97
#Mann= 3 , 0 , 0
    10.1      .1       0   435.2    .045       0   445.2      .1       0
#XS Ineff= 2 , 0
          410.93 1683.65
Permanent Ineff=
       F       F
Bank Sta=435.2,445.2
XS Rating Curve= 0 ,0
Exp/Cntr=0.3,0.1

Type RM Length L Ch R = 1 ,12449.7 ,64.4,65,65.8
XS GIS Cut Line= 4
     1788707.677      124167.723     1788333.566      124298.365
     1788104.942      124470.575     1787947.578      124568.557
#Sta/Elev= 30
     9.9 1893.07    39.6 1886.92    59.4 1881.23    69.3 1877.61    79.3 1873.02
    89.2 1867.76     109 1855.98   178.3 1812.59   198.1 1800.64   287.3 1750.35
   406.1 1675.44     416 1670.17   425.9 1667.54   435.7 1666.63   470.2 1665.79
   475.2 1665.74   480.2 1665.79     495 1665.95   504.8 1666.57   514.7 1670.45
   534.4 1681.24   554.2 1689.79   573.9 1697.73   633.1 1720.06   672.6 1733.48
     702 1741.58   731.3 1748.87   799.6 1764.53   848.4 1776.71   867.9  1780.6
#Mann= 3 , 0 , 0
     9.9      .1       0   470.2    .045       0   480.2      .1       0
#XS Ineff= 2 , 0
          454.02 1680.83
Permanent Ineff=
       F       F
Bank Sta=470.2,480.2
XS Rating Curve= 0 ,0
Exp/Cntr=0.3,0.1

Type RM Length L Ch R = 1 ,12384.6 ,102.8,122.1,138.9
XS GIS Cut Line= 4
     1788681.996      124137.452     1788286.151      124256.267
     1788125.395      124369.369     1787929.157       124490.68
#Sta/Elev= 30
    10.1 1902.17    60.5 1888.23    80.6 1880.48   100.8 1870.16     131 1851.37
   141.1 1846.24   151.2 1842.32   161.3 1837.37   171.4 1829.17   191.5 1808.98
   201.6 1801.71   262.1    1766   292.3  1747.3   332.6 1721.26   403.2    1674
   413.3 1668.37   423.1 1665.76   432.9 1665.08   506.6 1663.56   511.6 1663.52
  515.38 1664.95   521.4 1667.23   541.1 1677.84   590.2 1696.33   619.9 1705.79
     660 1716.24   730.2 1732.45   780.4 1738.21   810.5 1743.44   840.6 1745.48
#Mann= 3 , 0 , 0
    10.1      .1       0   506.6    .045       0  515.38      .1       0
Bank Sta=506.6,515.38
XS Rating Curve= 0 ,0
Exp/Cntr=0.3,0.1

Type RM Length L Ch R = 1 ,12262.5 ,324.7,321.9,319.1
XS GIS Cut Line= 4
     1788662.071       124096.38     1788272.266      124248.205
       1788001.9      124213.996     1787718.954      124313.211
#Sta/Elev= 30
      10 1906.09    39.8 1897.83    59.8 1891.14    99.6 1872.73   119.5 1865.93
   129.5 1861.48   139.4 1855.18   149.4 1846.93   169.3 1827.26   179.3 1818.47
   189.2 1811.26   278.9 1754.97   308.8 1735.45   398.4 1674.54   408.4  1668.9
   418.3 1665.63   428.4 1664.58   499.1 1661.38   554.6 1657.78   559.6 1657.49
   564.6 1657.51   579.8 1658.54   620.2 1665.77   650.5 1670.11   720.8 1683.33
   800.8 1691.47   840.8 1697.39   910.7 1710.98   960.7 1724.23   990.7 1731.19
#Mann= 3 , 0 , 0
       0      .1       0   554.6    .045       0   564.6      .1       0
Bank Sta=554.6,564.6
XS Rating Curve= 0 ,0
Exp/Cntr=0.3,0.1

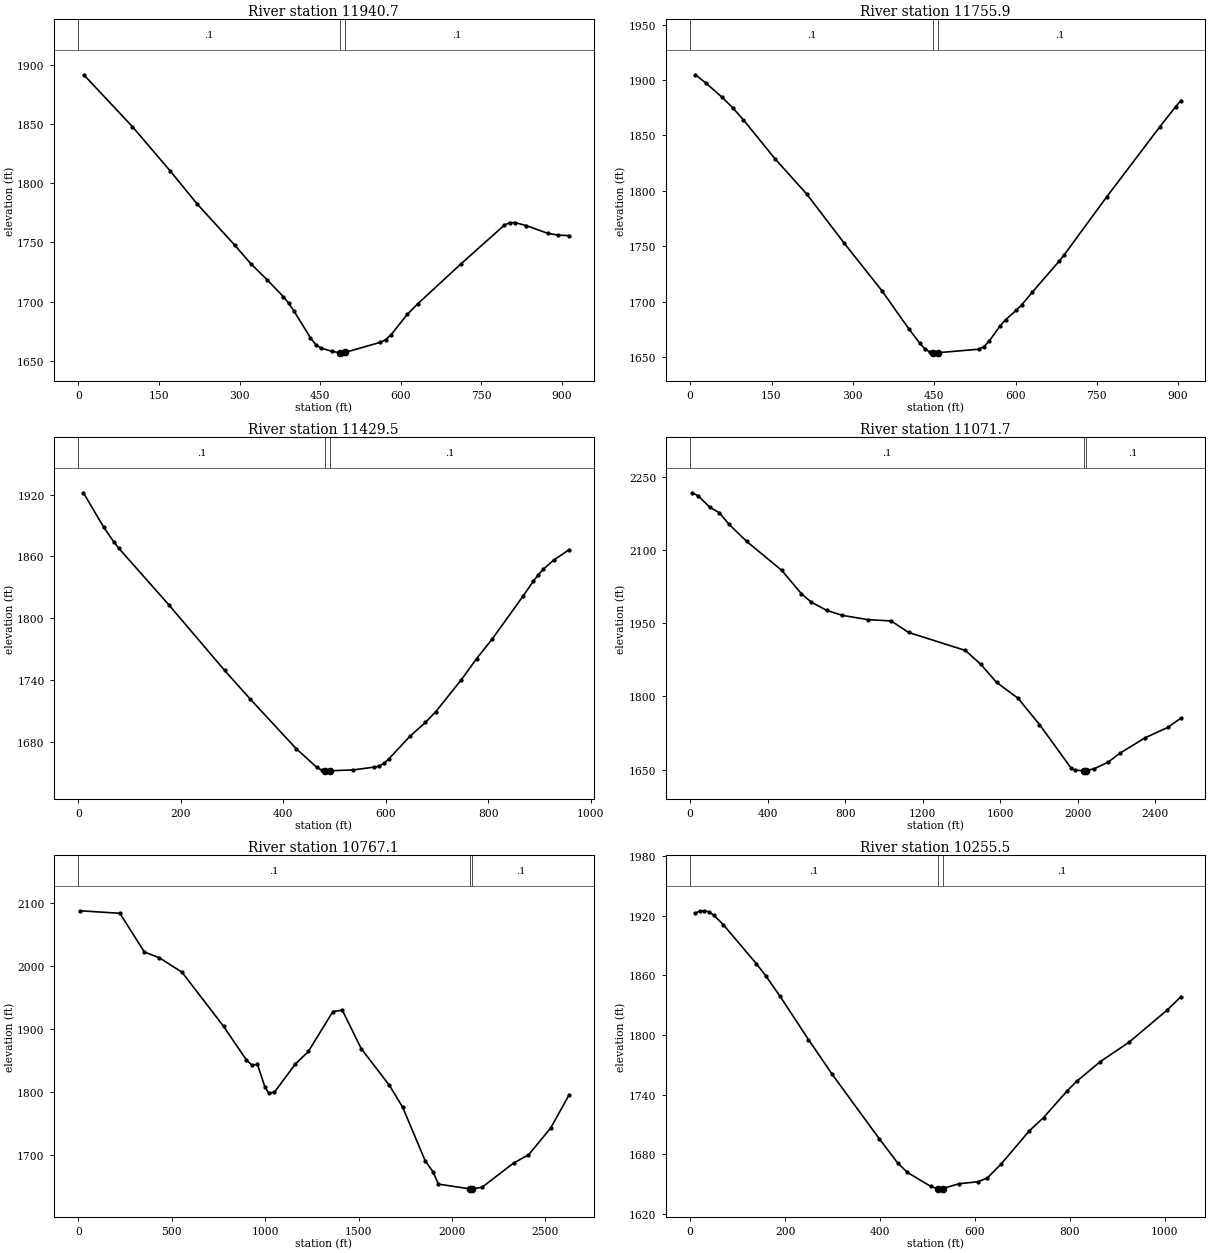
Type RM Length L Ch R = 1 ,11940.7 ,183.2,184.7,186.3
XS GIS Cut Line= 4
     1788684.164      123976.138     1788316.707       123922.69
      1788076.19      123929.371     1787788.906      124019.565
#Sta/Elev= 30
      10 1891.34   100.4 1847.66   170.6 1810.36   220.8 1782.47     291 1747.58
   321.1 1731.82   351.3 1718.36   381.3 1704.23   391.4  1698.6   401.4 1691.88
   431.5 1669.75   441.5 1663.75   451.5  1660.9   471.6 1658.08   486.6 1656.91
   491.6 1656.82   496.6 1657.23   561.8  1665.7   571.8 1667.98   581.9 1672.13
   611.9 1689.28     632 1698.42   712.3 1732.06   792.6 1764.53   802.6 1766.64
   812.7 1766.65   832.7  1764.2   872.9 1757.68     893 1756.08     913 1755.71
#Mann= 3 , 0 , 0
       0      .1       0   486.6    .045       0   496.6      .1       0
Bank Sta=486.6,496.6
XS Rating Curve= 0 ,0
Exp/Cntr=0.3,0.1

Type RM Length L Ch R = 1 ,11755.9 ,323.7,326.4,329.2
XS GIS Cut Line= 4
     1788677.986      123826.272     1788474.493      123757.098
     1788058.813      123736.314     1787788.622      123780.851
#Sta/Elev= 30
     9.8 1904.75    29.3 1897.19    58.6  1884.6    78.2 1875.12    97.7 1864.37
   156.3  1829.1   214.9 1797.18   284.3 1752.73   353.7 1709.92   403.2 1675.62
     423 1662.89   432.9  1657.4   442.8  1654.5   447.8 1654.22   452.8 1653.94
   457.8 1654.11     532  1657.2   541.9 1659.57   551.9 1664.79   571.7 1678.28
   581.6 1683.79   601.4 1692.29   611.3  1697.1   631.1 1708.71     680 1736.36
   689.8 1742.32     768  1794.5   865.8 1857.56   895.2 1875.91     905 1881.42
#Mann= 3 , 0 , 0
       0      .1       0   447.8    .045       0   457.8      .1       0
Bank Sta=447.8,457.8
XS Rating Curve= 0 ,0
Exp/Cntr=0.3,0.1

Type RM Length L Ch R = 1 ,11429.5 ,356,357.8,359.7
XS GIS Cut Line= 4
     1788757.655      123568.595     1788433.625      123451.677
     1788116.276      123391.548     1787825.651      123398.229
#Sta/Elev= 30
     9.8 1921.96    49.2 1888.68    68.9  1874.4    78.7 1868.11   177.2 1812.64
   285.4 1749.23   334.6 1721.85   425.2  1673.1   465.6 1654.86   475.7 1651.94
   480.8 1651.72   485.8 1651.51   490.8 1651.59   536.3 1652.38   576.6 1655.06
   586.7 1656.07   596.8 1658.78   606.9  1663.5   647.3 1685.08   677.5 1698.54
   697.5 1708.82   747.7 1740.08   777.7 1760.74   807.8 1779.54     868 1821.25
     888 1835.74     898  1842.2   908.1 1847.71   928.1 1856.47   958.2 1866.57
#Mann= 3 , 0 , 0
       0      .1       0   480.8    .045       0   490.8      .1       0
Bank Sta=480.8,490.8
XS Rating Curve= 0 ,0
Exp/Cntr=0.3,0.1

Type RM Length L Ch R = 1 ,11071.7 ,327.6,304.6,281.5
XS GIS Cut Line= 4
     1790156.244      124045.757     1788657.202      123158.216
     1788191.047      123024.605     1787902.246      123123.723
#Sta/Elev= 30
    10.1 2217.38    40.3 2211.42   100.7 2187.98     151 2176.27   201.4 2152.35
     292 2117.57   473.3 2058.04     574 2010.43   624.3 1993.31   704.9  1976.1
   785.4 1966.05   916.4 1957.33  1037.2 1954.56  1127.8 1930.95  1419.8 1894.11
  1500.4 1865.48    1581 1828.69  1691.7 1796.13  1802.7 1742.26  1964.3 1653.72
  1984.5 1648.85  2030.1 1647.36  2035.1 1647.27  2040.1 1647.28  2085.6 1651.69
  2156.3 1664.92  2216.9 1683.17  2345.2 1714.46  2463.4 1736.13  2532.3 1755.21
#Mann= 3 , 0 , 0
       0      .1       0  2030.1    .045       0  2040.1      .1       0
Bank Sta=2030.1,2040.1
XS Rating Curve= 0 ,0
Exp/Cntr=0.3,0.1

Type RM Length L Ch R = 1 ,10767.1 ,502.8,511.6,519
XS GIS Cut Line= 4
     1789497.043      121079.351     1788574.066      122608.926
     1788256.368      122962.253     1787892.481       122997.94
#Sta/Elev= 30
    10.1 2088.16     222 2084.17   353.3 2022.64     434 2013.41   555.1 1990.41
   777.2 1904.57   898.3 1851.67   928.6 1842.95   958.8 1843.94   999.2 1807.63
  1019.4 1798.45  1049.7 1799.85  1160.7 1844.26  1231.4  1864.6  1362.6 1928.07
    1413  1930.2    1514 1869.25  1665.4  1810.6    1736 1776.11  1857.2 1690.53
  1897.7 1673.76    1928 1653.72  2094.9 1646.31  2099.9 1646.27  2104.9 1646.28
  2160.5 1648.57  2330.8 1687.41  2409.9 1700.24  2528.4 1742.77  2627.3 1795.59
#Mann= 3 , 0 , 0
       0      .1       0  2094.9    .045       0  2104.9      .1       0
Bank Sta=2094.9,2104.9
XS Rating Curve= 0 ,0
Exp/Cntr=0.3,0.1

Type RM Length L Ch R = 1 ,10255.5 ,203.1,200.7,199.7
XS GIS Cut Line= 4
     1788535.467      122267.475     1788204.299      122377.735
     1787877.236      122541.267     1787650.522      122766.122
#Sta/Elev= 30
      10  1922.3    19.9 1924.42    29.9 1924.79    39.9  1923.6    49.9 1920.26
    69.8 1910.86   139.6 1871.54   159.6 1859.22   189.5  1838.8   249.3 1795.36
   299.2 1760.43   398.5 1695.61     438 1670.88   457.8 1661.83   507.2  1647.7
   521.9 1645.45   526.9 1645.31   531.9 1645.61   566.5 1650.41     606 1652.42
   625.8 1656.09   655.4 1670.35   714.7 1703.65   744.6  1716.9   794.5 1743.83
   814.5 1753.42   864.4 1773.26   924.3  1792.5  1004.1 1824.59    1034 1838.31
#Mann= 3 , 0 , 0
       0      .1       0   521.9    .045       0   531.9      .1       0
Bank Sta=521.9,531.9
XS Rating Curve= 0 ,0
Exp/Cntr=0.3,0.1

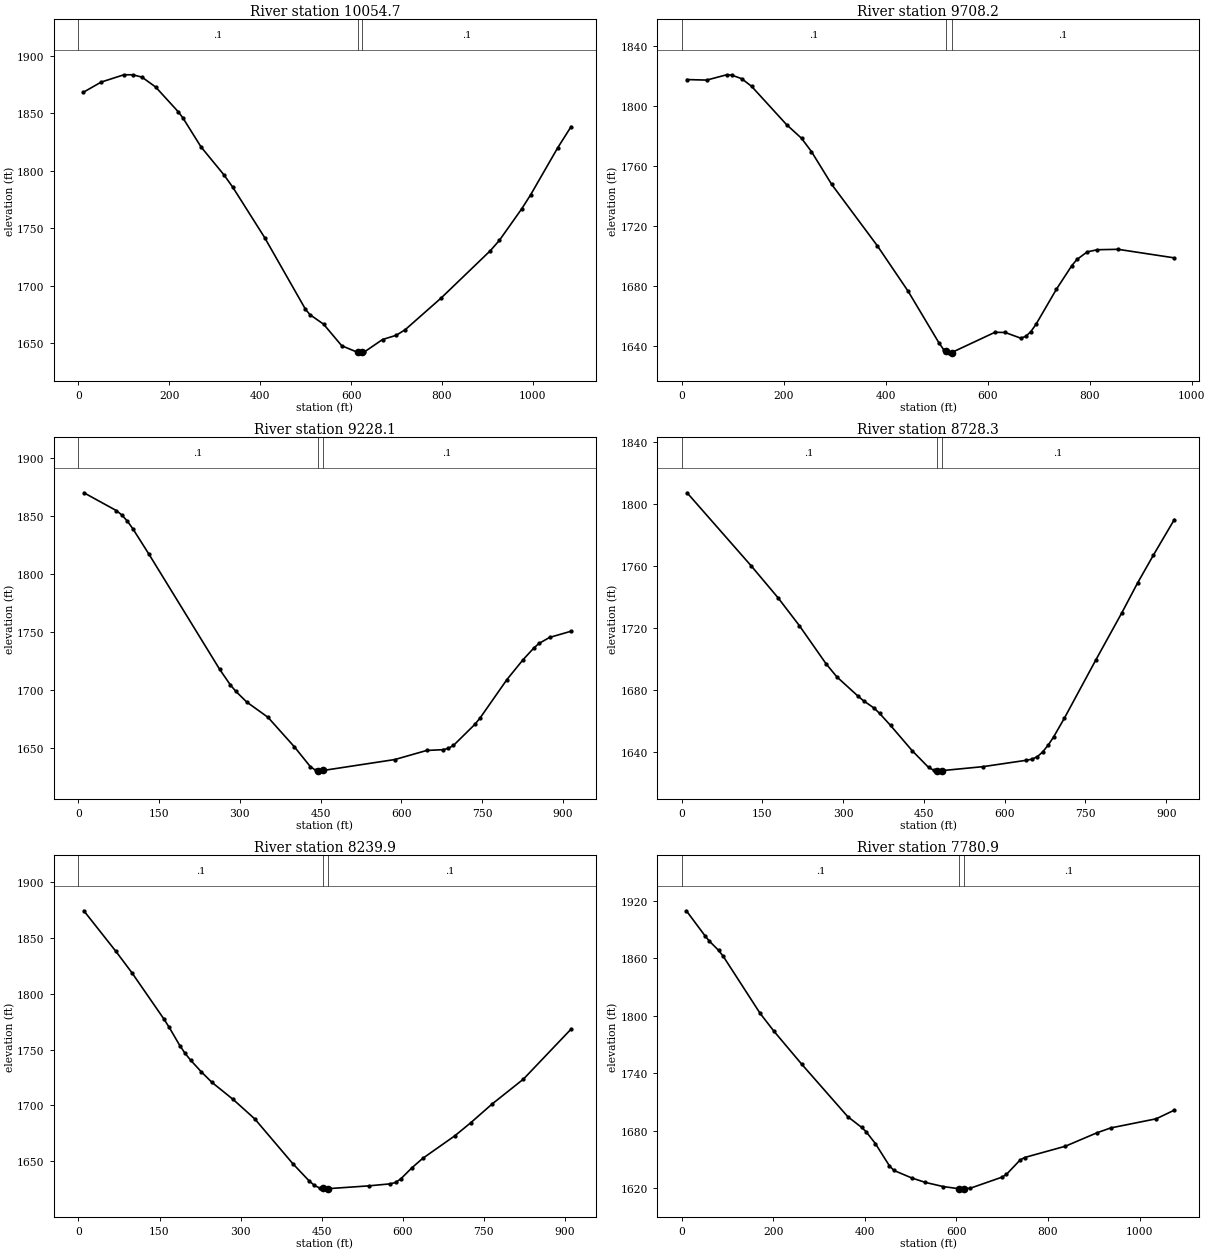
Type RM Length L Ch R = 1 ,10054.7 ,327.3,346.5,365.7
XS GIS Cut Line= 4
     1788549.944      122160.313     1788083.508      122214.204
      1787873.52      122329.419      1787576.19      122557.991
#Sta/Elev= 30
      10 1868.18      50 1877.21    99.9 1883.56   119.9 1883.55   139.9 1881.46
   169.8 1872.91   219.8 1851.26   229.8 1846.02   269.7 1820.77   319.7 1796.67
   339.7 1785.62   409.6 1741.92   499.5 1679.51   509.5 1674.77   539.4 1666.52
   579.3 1647.75   614.2 1642.03   619.2 1641.58   624.2 1641.97   629.2 1642.37
   669.1 1653.17   699.1 1656.84   718.9 1661.68   797.9 1689.22   906.4  1730.5
   926.2 1739.44   975.5 1766.96   995.3 1779.31  1054.5 1819.95  1084.1 1838.48
#Mann= 3 , 0 , 0
       0      .1       0   614.2    .045       0   624.2      .1       0
Bank Sta=614.2,624.2
XS Rating Curve= 0 ,0
Exp/Cntr=0.3,0.1

Type RM Length L Ch R = 1 ,9708.2  ,489,480.1,471.2
XS GIS Cut Line= 4
     1788427.048      122078.269     1788143.541      122065.573
     1787846.635      121920.535     1787537.359      121752.802
#Sta/Elev= 30
     9.8 1817.55    48.9  1817.2    88.1 1820.74    97.9 1820.54   117.4 1818.16
     137 1813.03   205.5 1787.51   234.9 1778.39   254.4 1769.49   293.8 1747.75
   383.9 1706.53     444 1676.33   504.1 1642.09   514.1 1637.18   519.1 1636.22
   524.1 1635.26   529.1 1635.42   614.2 1648.96   634.3 1648.84   664.5 1645.08
   674.5  1646.2   684.6 1649.38   694.6 1654.22   734.9 1677.76     765 1693.45
   775.1 1697.56   795.2 1702.62   815.3 1704.04   855.5 1704.32   966.1  1698.6
#Mann= 3 , 0 , 0
       0      .1       0   519.1    .045       0   529.1      .1       0
Bank Sta=519.1,529.1
XS Rating Curve= 0 ,0
Exp/Cntr=0.3,0.1

Type RM Length L Ch R = 1 ,9228.1  ,504.4,499.8,495.1
XS GIS Cut Line= 4
     1788586.608      121591.598     1788276.682      121549.432
     1787962.424      121540.036     1787682.996         121469.
#Sta/Elev= 30
    10.1 1869.71    70.6 1854.35    80.7 1850.54    90.8 1845.35   100.9 1838.88
   131.2 1816.72   262.3 1717.97   282.5  1704.4   292.6 1698.93   312.8 1689.78
   352.1 1676.72   401.2 1651.33   430.7 1634.39   440.5 1631.18   445.3 1630.93
   450.3 1630.67   455.3 1631.03   587.9 1640.38   647.1 1648.19   676.9 1648.85
   686.8 1649.91   696.8 1652.48   736.5 1670.57   746.5 1676.21   796.2 1709.13
     826  1726.1   845.9 1736.12   855.8 1740.18   875.7 1745.39   915.5  1750.7
#Mann= 3 , 0 , 0
       0      .1       0   445.3    .045       0   455.3      .1       0
Bank Sta=445.3,455.3
XS Rating Curve= 0 ,0
Exp/Cntr=0.3,0.1

Type RM Length L Ch R = 1 ,8728.3  ,496.3,488.5,480.6
XS GIS Cut Line= 4
     1788569.684      121007.515     1788202.665      121027.576
     1787876.318      121094.665     1787662.348      121081.801
#Sta/Elev= 30
     9.9 1807.53   129.1 1760.35   178.8 1739.83   218.6 1721.77   268.2 1697.16
   288.1 1688.78   327.8 1676.22   337.8 1673.33   357.6 1668.55   367.6 1665.17
   387.8 1657.45   428.1 1641.12   458.4 1630.38   468.5 1628.44   473.6 1628.29
   478.6 1628.14   483.6 1628.29   559.4 1630.83   640.2 1634.96   650.3 1635.64
   660.4 1637.24   670.4 1640.33   680.5 1644.65   690.6 1649.91   710.5 1661.94
   768.9 1699.49   817.7 1730.22   846.9 1749.44   876.1 1767.28   915.1 1790.29
#Mann= 3 , 0 , 0
       0      .1       0   473.6    .045       0   483.6      .1       0
Bank Sta=473.6,483.6
XS Rating Curve= 0 ,0
Exp/Cntr=0.3,0.1

Type RM Length L Ch R = 1 ,8239.9  ,430.3,459,487.5
XS GIS Cut Line= 4
     1788339.504      120450.362     1788058.704      120506.649
     1787751.615      120714.615     1787535.978      120850.467
#Sta/Elev= 30
     9.9 1874.14    69.1 1837.94    98.8 1818.79     158 1777.41   167.9  1769.9
   187.6 1753.54   197.5 1746.47   207.4  1740.6   227.1 1730.19   246.9 1720.69
   286.4 1705.32   326.5 1687.87   396.6    1648   426.7 1632.64   436.7 1628.45
   446.8 1626.02   451.8 1625.68   456.8 1625.35   461.8 1625.49     537    1628
   577.1 1629.81   587.1 1631.03   597.1 1634.41   617.2 1644.12   637.2 1652.55
   696.5  1672.7   725.9 1684.32   765.1 1700.95   823.9 1723.56   912.1 1768.31
#Mann= 3 , 0 , 0
       0      .1       0   451.8    .045       0   461.8      .1       0
Bank Sta=451.8,461.8
XS Rating Curve= 0 ,0
Exp/Cntr=0.3,0.1

Type RM Length L Ch R = 1 ,7780.9  ,561.3,542.9,524.6
XS GIS Cut Line= 4
     1788333.566       120355.35      1787870.38      120340.504
     1787692.232      120171.263     1787327.028      120206.893
#Sta/Elev= 30
    10.1 1909.65    50.4 1883.79    60.4 1877.93    80.6 1868.26    90.7 1862.07
   171.3 1802.44   201.5  1783.8   261.9  1749.5   362.7 1694.58   392.9 1683.42
     403 1678.74   423.1 1666.41   453.3 1643.53   463.4 1638.45   502.7 1630.51
   532.2 1625.92   571.5 1621.55   605.9 1619.33   610.9 1619.21   615.9 1619.22
   630.5 1619.89   699.3 1631.37   709.1 1634.23   738.9  1649.2   748.8 1651.92
   838.1 1663.73   907.5 1677.86   937.2 1682.84  1036.4 1692.36  1076.1 1701.43
#Mann= 3 , 0 , 0
       0      .1       0   605.9    .045       0   615.9      .1       0
Bank Sta=605.9,615.9
XS Rating Curve= 0 ,0
Exp/Cntr=0.3,0.1

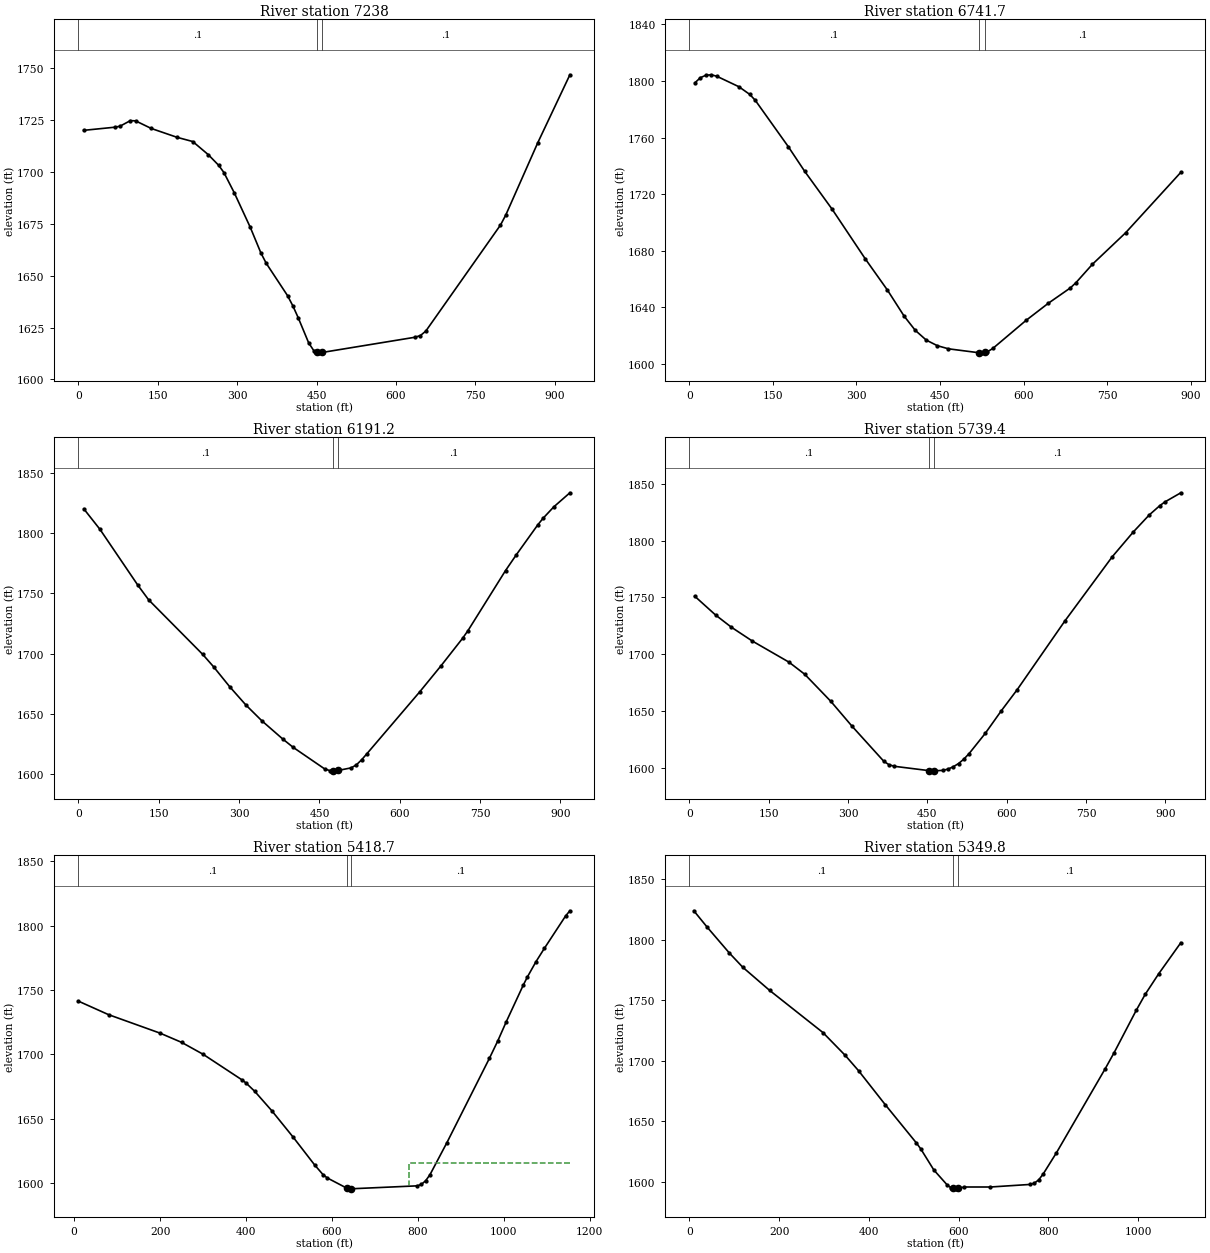
Type RM Length L Ch R = 1 ,7238    ,476.6,496.3,516
XS GIS Cut Line= 4
     1788280.588       119701.77     1787986.326      119714.507
     1787647.695      119758.553     1787365.627      119835.751
#Sta/Elev= 30
     9.8 1720.02    68.7 1721.53    78.5 1722.01    98.2 1724.71     108 1724.59
   137.5 1720.94   186.5 1716.65     216 1714.63   245.4 1708.29   265.1 1703.14
   274.9 1699.67   294.5 1689.91   324.7 1673.29   344.8 1660.92   354.8 1655.98
     395 1640.42     405 1635.53   415.1 1629.83   435.1 1617.57   445.2  1613.7
   450.2 1613.27   455.2 1612.84   460.2 1613.01     636 1620.36   646.1 1621.17
   656.2 1623.29   797.4 1674.41   807.5  1679.3     868 1714.15   928.5 1746.79
#Mann= 3 , 0 , 0
       0      .1       0   450.2    .045       0   460.2      .1       0
Bank Sta=450.2,460.2
XS Rating Curve= 0 ,0
Exp/Cntr=0.3,0.1

Type RM Length L Ch R = 1 ,6741.7  ,561.8,550.4,539.1
XS GIS Cut Line= 4
      1788307.97      119576.825     1788036.652       119458.67
     1787793.183      119209.262     1787555.651      119194.417
#Sta/Elev= 30
     9.9  1798.7    19.7 1802.34    29.6 1804.07    39.5  1804.4    49.3 1803.35
    88.8 1795.98   108.5 1790.51   118.4 1786.31   177.6 1753.61   207.2  1736.1
   256.5  1709.3   315.8 1674.35   355.7 1652.22   385.6 1633.86   405.5 1623.85
   425.4 1616.89   445.3 1612.95   465.2 1610.75     520 1607.96     525  1607.9
     530 1608.25   534.9 1608.59   544.9 1611.01   604.6 1630.85   644.5 1642.93
   684.1 1653.78   694.1 1657.45   723.8 1670.53   783.3 1692.73   882.5 1735.47
#Mann= 3 , 0 , 0
       0      .1       0     520    .045       0     530      .1       0
Bank Sta=520,530
XS Rating Curve= 0 ,0
Exp/Cntr=0.3,0.1

Type RM Length L Ch R = 1 ,6191.2  ,449,451.8,454.6
XS GIS Cut Line= 4
     1788588.912       119078.62     1788297.861      118939.015
     1788021.806      118870.781     1787718.754      118803.543
#Sta/Elev= 30
    10.1 1819.97    40.4 1802.91     111  1756.7   131.1  1744.6     232 1699.41
   252.2  1689.2   282.5 1672.56   312.7 1657.43   342.4 1644.38   381.6 1629.22
   401.2 1622.27   460.1 1604.37   469.9 1603.02   474.7 1602.95   479.7 1602.88
   484.7 1603.19   509.1 1605.34   518.9 1607.81   528.7 1612.02   538.5 1617.01
   637.2 1668.33   677.3 1690.12   717.3 1712.75   727.3 1719.07   797.4 1768.85
   817.4 1781.84   857.5 1806.65   867.5 1812.18   887.5 1821.64   917.6 1833.33
#Mann= 3 , 0 , 0
       0      .1       0   474.7    .045       0   484.7      .1       0
Bank Sta=474.7,484.7
XS Rating Curve= 0 ,0
Exp/Cntr=0.3,0.1

Type RM Length L Ch R = 1 ,5739.4  ,329.3,320.7,311.7
XS GIS Cut Line= 4
     1788701.739      118728.262     1788458.271      118540.944
     1788149.479      118416.502     1787862.844      118377.629
#Sta/Elev= 30
     9.9 1751.16    49.5 1734.55    79.3 1723.84   118.9 1711.66   188.3 1693.06
     218 1682.44   267.6 1658.49   307.2 1636.87   367.7 1605.79   377.8  1602.7
   387.9 1601.37   453.5 1597.55   458.5 1597.39   463.5 1597.41   478.7 1597.78
   488.8 1598.87   498.9 1600.94     509 1603.81     519 1607.66   529.1 1612.64
   559.4 1630.29   589.7 1650.13   619.9 1668.81   709.9 1729.17   799.7 1785.82
   839.6 1807.68   869.5 1822.54   889.5 1830.74   899.4  1834.1   929.4 1842.11
#Mann= 3 , 0 , 0
       0      .1       0   453.5    .045       0   463.5      .1       0
Bank Sta=453.5,463.5
XS Rating Curve= 0 ,0
Exp/Cntr=0.3,0.1

Type RM Length L Ch R = 1 ,5418.7  ,74.7,68.9,63.1
XS GIS Cut Line= 4
     1789072.881      118247.262     1788615.217      118199.559
     1788247.461      118214.601     1787950.547      118348.212
#Sta/Elev= 30
      10 1741.33      80 1730.84   200.1 1716.43   250.1 1709.27   300.1 1700.01
   390.1 1680.21   400.1 1677.64   420.1 1671.25   460.1 1656.05   509.9 1635.46
   559.6 1613.96   579.5 1606.27   589.5 1603.73   634.2 1595.91   639.2 1595.31
   644.2 1595.34   798.4 1597.64   808.3 1598.79   818.3 1601.71   828.2 1606.33
   867.7 1631.33   966.3 1696.72   986.1 1710.49  1005.8 1725.37  1045.3 1753.82
  1055.1 1760.28  1074.9 1772.05  1094.6 1782.51  1143.9 1807.65  1153.8 1811.64
#Mann= 3 , 0 , 0
      10      .1       0   634.2    .045       0   644.2      .1       0
#XS Ineff= 2 , 0
                          779.48         1615.44
Permanent Ineff=
       F       F
Bank Sta=634.2,644.2
XS Rating Curve= 0 ,0
Exp/Cntr=0.3,0.1

Type RM Length L Ch R = 1 ,5349.8  ,140.8,129.7,118.5
XS GIS Cut Line= 4
     1789007.785      118032.311     1788508.365      118113.612
      1788287.69      118187.944     1787953.195      118311.058
#Sta/Elev= 30
     9.9 1823.82    39.7 1810.26    89.3 1788.83   119.1 1777.12   178.6 1758.11
   297.6 1723.21   347.3 1704.34     377 1691.68   436.5 1663.61     506 1631.94
   515.7 1627.04   544.8 1609.65   573.9 1597.54   583.6 1594.71   588.3 1594.39
   593.3 1594.05   598.3 1594.43   612.7 1595.57   670.9 1595.57   758.7 1597.67
   768.6 1598.69   778.5 1601.47   788.4 1606.26   818.1 1623.88     927 1693.47
   946.8 1706.71   996.3 1741.86  1016.1 1754.89  1045.8 1771.69  1095.3 1797.45
#Mann= 3 , 0 , 0
       0      .1       0   588.3    .045       0   598.3      .1       0
Bank Sta=588.3,598.3
XS Rating Curve= 0 ,0
Exp/Cntr=0.3,0.1

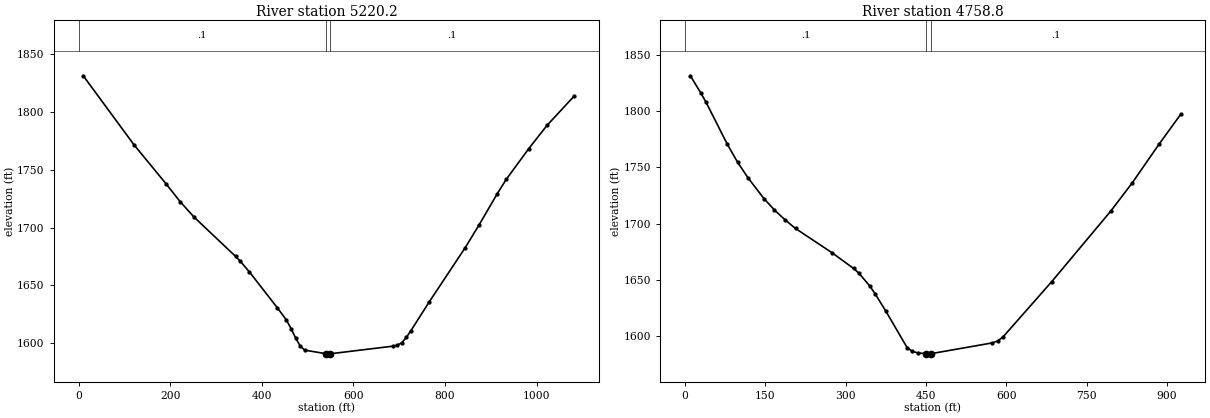
Type RM Length L Ch R = 1 ,5220.2  ,466.6,461.4,456.2
XS GIS Cut Line= 4
     1788811.597      117861.274     1788462.645      117912.893
     1788247.461      118167.095      1787870.38       118288.83
#Sta/Elev= 30
    10.1 1831.41   120.9  1771.7   191.5 1737.67   221.7  1722.5     252 1709.17
   342.7 1675.16   352.7 1671.14   372.9 1661.73   433.5 1630.92   453.7 1620.08
   463.8 1612.73   473.9 1604.54     484 1597.51     494 1594.03   539.5 1591.04
   544.5 1590.87   549.5 1590.93   685.8 1597.49   695.7 1598.25   705.6 1600.49
   715.5 1605.08   725.4 1610.83     765 1635.51   844.3 1682.85     874 1702.16
   913.6 1729.07   933.5 1741.69     983 1768.48  1022.6 1788.43    1082 1813.88
#Mann= 3 , 0 , 0
       0      .1       0   539.5    .045       0   549.5      .1       0
Bank Sta=539.5,549.5
XS Rating Curve= 0 ,0
Exp/Cntr=0.3,0.1

Type RM Length L Ch R = 1 ,4758.8  ,4766.7,4758.8,4751
XS GIS Cut Line= 4
      1788246.19      117379.741     1788079.321      117610.515
     1787944.609      117899.872     1787760.959      118163.629
#Sta/Elev= 30
     9.8 1831.49    29.5 1816.12    39.3 1807.83    78.6 1770.86    98.2 1754.52
   117.8 1740.62   147.3 1722.34   166.9 1712.25   186.6  1703.5   206.2  1695.8
     275 1674.05   314.7 1660.28   324.7 1656.03   344.6 1644.85   354.6 1637.95
   374.6  1622.6   414.5 1590.03   424.4 1586.55   434.4 1585.31   449.3 1584.53
   454.3 1584.42   459.3 1584.58     574 1594.16     584 1595.92     594 1599.61
   684.3 1648.37   794.8 1711.18     835 1736.33   885.2 1770.78   925.4 1797.17
#Mann= 3 , 0 , 0
       0      .1       0   449.3    .045       0   459.3      .1       0
Bank Sta=449.3,459.3
XS Rating Curve= 0 ,0
Exp/Cntr=0.3,0.1

Chan Stop Cuts=-1
Use User Specified Reach Order=0